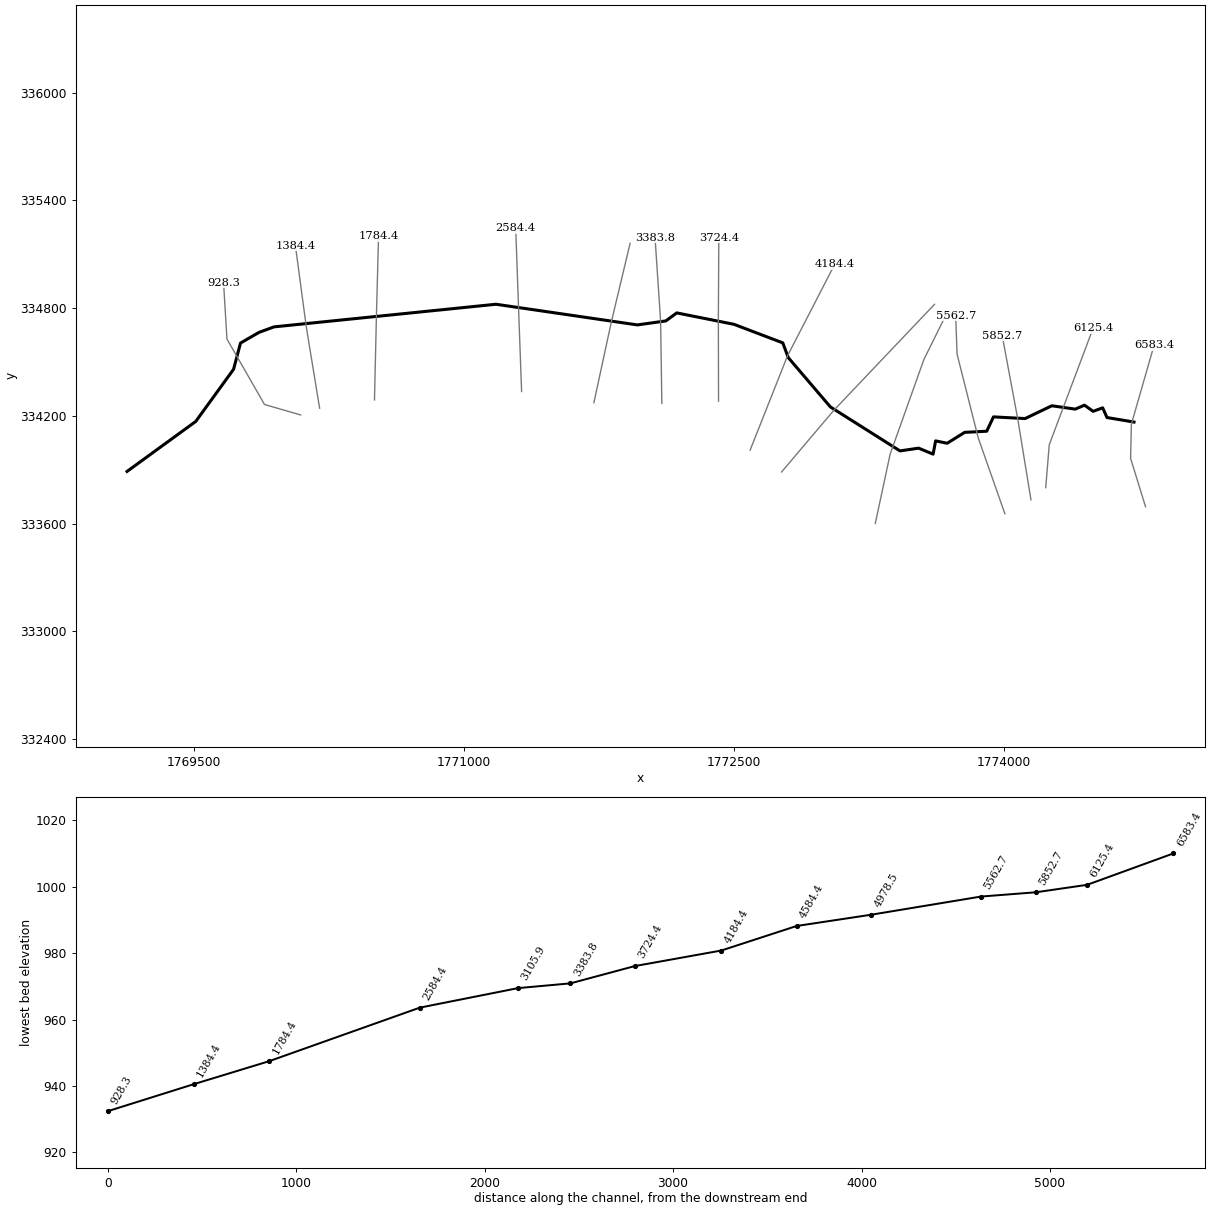
--- SppRn.prj (project) ---

Proj Title=SppRn
Current Plan=p01
Geom File=g01
Flow File=f01
Plan File=p01
DSS Export Rating Curves=0
DSS Export Rating Curve Sorted=0
DSS Export Volume Flow Curves=0
DXF OffsetX=0
DXF OffsetY=0
DXF ScaleX=0
DXF ScaleY=0

--- SppRn.p01 (plan) ---

Plan Title=Floodplain
Program Version=4.00
Geom File=g01
Flow File=f01
K Sum by GR=0
Std Step Tol=0.01
Critical Tol=0.01
Num of Std Step Trials=20
Max Error Tol=0.3
Flow Tol Ratio=0.001
Split Flow NTrial=30
Split Flow Tol=0.02
Split Flow Ratio=0.02
Log Output Level=0
Friction Slope Method=1
Unsteady Friction Slope Method=2
Unsteady Bridges Friction Slope Method=1
Global Log Level=0
CheckData=False
Run HTab=0
Run UNet=0
Run PostProcess=0
UNET Theta=0
UNET Theta Warmup=0
UNET ZTol=0
UNET ZSATol=0
UNET MxIter=0
UNET MaxInSteps=0
UNET DtIC=0
UNET DtMin=0
UNET MaxCRTS=0
UNET WFStab=0
UNET SFStab=0
UNET WFX=0
UNET SFX=0
UNET DSS MLevel=0
UNET DZMax Abort=0
UNET Convert EG Bridges=0
UNET Use Existing IB Tables=0
UNET Froude Limit=0
UNET Froude Power=0
Write IC File=0
Echo Input=False
Echo Output=False
Write Detailed=0

--- SppRn.f01 (steady flow) ---

Flow Title=NFF Regression Equation
Program Version=4.00
Number of Profiles=1
Profile Names=P100yr
River Rch & RM=SppRn,Main      ,6583.4
660.1297
River Rch & RM=SppRn,Main      ,6125.4
673.7129
River Rch & RM=SppRn,Main      ,5852.7
751.6076
River Rch & RM=SppRn,Main      ,3724.4
828.2421
River Rch & RM=SppRn,Main      ,928.3
907.6610
Boundary for River Rch & Prof#=SppRn,Main      ,1
Up Type=0
Dn Type=3
Dn Slope=0.016617

--- SppRn.g01 (geometry) ---

Geom Title=USGS 3m DEM
Program Version=4.00

River Reach=SppRn     ,Main
Reach XY= 30
     1774724.523      334166.039     1774574.386      334191.183
     1774550.454      334245.282     1774497.401      334225.721
     1774449.448      334260.037     1774398.032      334237.960
     1774267.881      334256.724     1774119.468      334185.443
     1773943.824      334194.848     1773906.222      334115.025
     1773783.929      334108.636     1773686.416      334048.018
     1773622.341      334061.211     1773608.322      333987.313
     1773527.824      334020.721     1773424.360      334005.396
     1773037.630      334250.232     1772803.691      334524.854
     1772773.254      334606.849     1772502.004      334710.181
     1772184.081      334773.760     1772123.633      334729.104
     1771965.177      334706.883     1771179.720      334821.910
     1769946.997      334696.030     1769863.257      334665.361
     1769760.442      334605.838     1769721.882      334459.839
     1769511.588      334169.311     1769129.882      333891.061

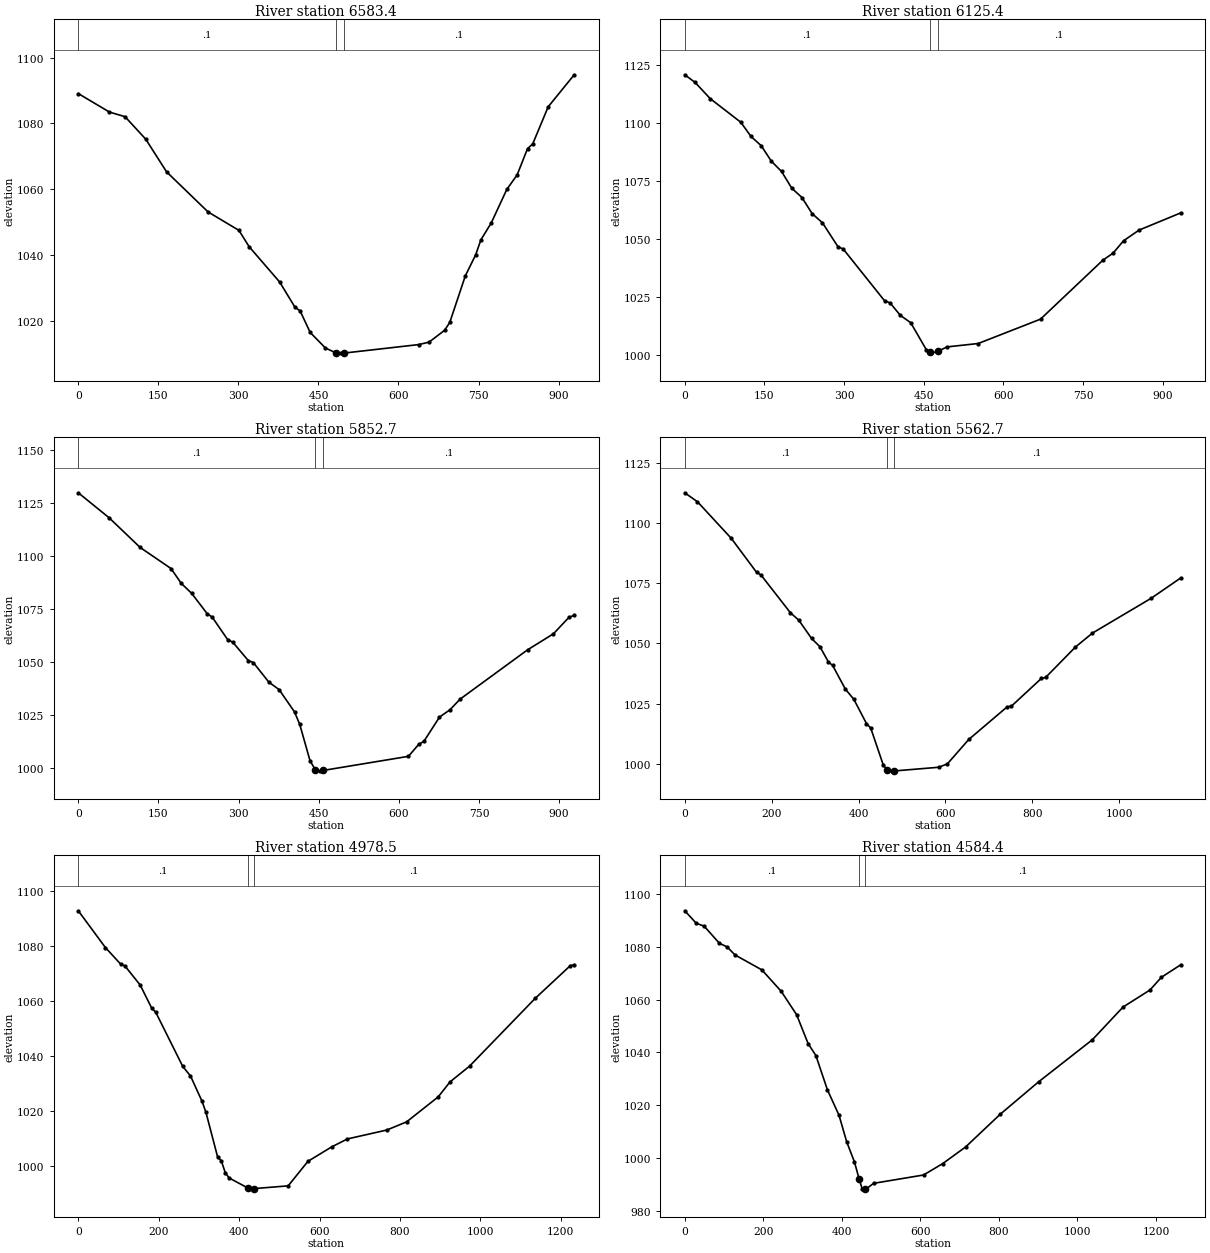
Type RM Length L Ch R = 1 ,6583.4,457.591,457.974,452.058
XS GIS Cut Line= 4
     1774788.709      333694.562     1774705.521      333963.962
     1774710.029      334154.709     1774835.985      334593.423
#Sta/Elev= 30
       0 1089.08    58.3 1083.45    87.5 1082.05   126.4 1075.19   165.3 1065.27
   243.1 1053.06   301.0 1047.44   320.1 1042.48   377.4 1031.70   406.0 1024.05
   415.5 1022.96   434.6 1016.36   463.2 1011.62   482.2 1010.20   492.2 1010.08
   497.2 1010.08   637.8 1012.68   657.3 1013.43   686.4 1017.03   696.1 1019.43
   725.2 1033.58   744.7 1040.03   754.4 1044.56   773.8 1049.70   802.9 1059.89
   822.4 1064.35   841.8 1072.33   851.5 1073.75   880.6 1085.08   929.2 1094.79
#Mann= 3 , 0 , 0
       0     0.1       0   482.2   0.045       0   497.2     0.1       0
Bank Sta=   482.2,   497.2
Exp/Cntr=0.3,0.1

Type RM Length L Ch R = 1 ,6125.4,260.761,272.744,285.185
XS GIS Cut Line= 3
     1774234.050      333800.907     1774253.688      334039.859
     1774497.779      334689.589
#Sta/Elev= 30
       0 1120.95    19.2 1117.71    48.0 1110.63   105.5 1100.44   124.7 1094.30
   143.9 1090.31   163.0 1083.60   182.2 1079.16   201.4 1071.94   220.6 1067.90
   239.8 1060.94   259.3 1056.96   288.6 1046.58   298.4 1045.62   376.6 1023.14
   386.4 1022.38   405.9 1016.95   425.5 1013.76   454.8 1002.11     461 1001.16
   464.6 1000.61     476 1001.32   493.9 1003.30   552.6 1004.77   669.9 1015.30
   787.2 1040.77   806.7 1043.87   826.3 1049.19   855.6 1053.82   933.8 1061.23
#Mann= 3 , 0 , 0
       0     0.1       0     461   0.045       0     476     0.1       0
Bank Sta=     461,     476
Exp/Cntr=0.3,0.1

Type RM Length L Ch R = 1 ,5852.7,284.446,290.006,292.381
XS GIS Cut Line= 3
     1774152.051      333733.113     1774079.142      334180.254
     1773992.263      334647.377
#Sta/Elev= 30
       0 1129.77    57.8 1117.95   115.7 1103.98   173.5 1094.02   192.8 1086.98
   212.1 1082.33   241.0 1072.77   250.6 1071.08   279.5 1060.47   289.2 1059.22
   318.1 1050.58   327.7 1049.59   356.7 1040.36   375.9 1036.85   404.8 1026.28
   414.5 1020.42   433.8 1003.23   443.7  998.99   453.0  998.36   458.7  998.70
   617.9 1005.34   637.3 1011.02   647.0 1012.45   676.1 1023.87   695.5 1027.29
   714.9 1032.40   840.9 1055.62   889.4 1063.20   918.5 1070.99   928.2 1071.92
#Mann= 3 , 0 , 0
       0     0.1       0   443.7   0.045       0   458.7     0.1       0
Bank Sta=   443.7,   458.7
Exp/Cntr=0.3,0.1

Type RM Length L Ch R = 1 ,5562.7,599.305,584.217,525.269
XS GIS Cut Line= 4
     1774007.107      333655.711     1773859.063      334077.804
     1773741.434      334544.524     1773733.845      334757.014
#Sta/Elev= 30
       0 1112.47    29.2 1108.76   107.0 1093.59   165.3 1079.48   175.0 1078.48
   243.1 1062.74   262.5 1059.64   291.7 1052.11   311.2 1048.62   330.6 1042.32
   340.3 1040.90   369.5 1031.09   389.0 1026.88   418.1 1016.81   427.9 1014.96
   457.1  999.47   466.4  997.52   476.8  997.08   481.4  997.14   584.8  998.69
   604.5 1000.12   653.6 1010.21   742.0 1023.74   751.8 1024.02   820.6 1035.50
   830.4 1035.91   899.1 1048.53   938.3 1054.32  1073.6 1068.77  1141.2 1077.15
#Mann= 3 , 0 , 0
       0     0.1       0   466.4   0.045       0   481.4     0.1       0
Bank Sta=   466.4,   481.4
Exp/Cntr=0.3,0.1

Type RM Length L Ch R = 1 ,4978.5,402.332,394.057,384.503
XS GIS Cut Line= 4
     1773286.992      333601.061     1773369.575      333986.736
     1773557.077      334514.021     1773680.722      334764.603
#Sta/Elev= 30
       0 1092.64    67.3 1079.32   105.8 1073.21   115.4 1072.72   153.9 1065.69
   182.8 1057.22   192.4 1055.87   259.7 1036.16   279.0 1032.69   307.8 1023.47
   317.5 1019.45   346.3 1003.39   355.9 1001.79   365.6  997.53   375.2  995.64
   422.1  991.97   433.7  991.59   437.1  991.78   522.1  992.78   571.1 1001.67
   630.1 1006.91   669.3 1009.81   767.5 1013.05   816.6 1016.01   895.1 1025.06
   924.6 1030.51   973.3 1036.25  1137.1 1060.93  1223.8 1072.71  1233.5 1073.09
#Mann= 3 , 0 , 0
       0     0.1       0   422.1   0.045       0   437.1     0.1       0
Bank Sta=   422.1,   437.1
Exp/Cntr=0.3,0.1

Type RM Length L Ch R = 1 ,4584.4,390.068,400,409.363
XS GIS Cut Line= 3
     1772766.533      333888.121     1773058.126      334232.898
     1773616.216      334821.521
#Sta/Elev= 30
       0 1093.66    29.4 1088.92    49.1 1087.87    88.3 1081.34   108.0 1079.98
   127.6 1076.97   196.3 1071.28   245.4 1063.19   284.7 1054.31   314.1 1043.34
   333.8 1038.84   363.2 1025.83   392.7 1016.21   412.3 1006.13   431.9  998.58
     444  992.03   451.6  988.37     459  988.24   461.3  988.21   480.9  990.41
   607.9  993.56   656.8  997.88   715.4 1004.22   803.4 1016.60   901.1 1028.88
  1037.9 1044.81  1116.1 1057.21  1184.5 1063.64  1213.8 1068.48  1262.7 1073.19
#Mann= 3 , 0 , 0
       0     0.1       0     444   0.045       0     459     0.1       0
Bank Sta=     444,     459
Exp/Cntr=0.3,0.1

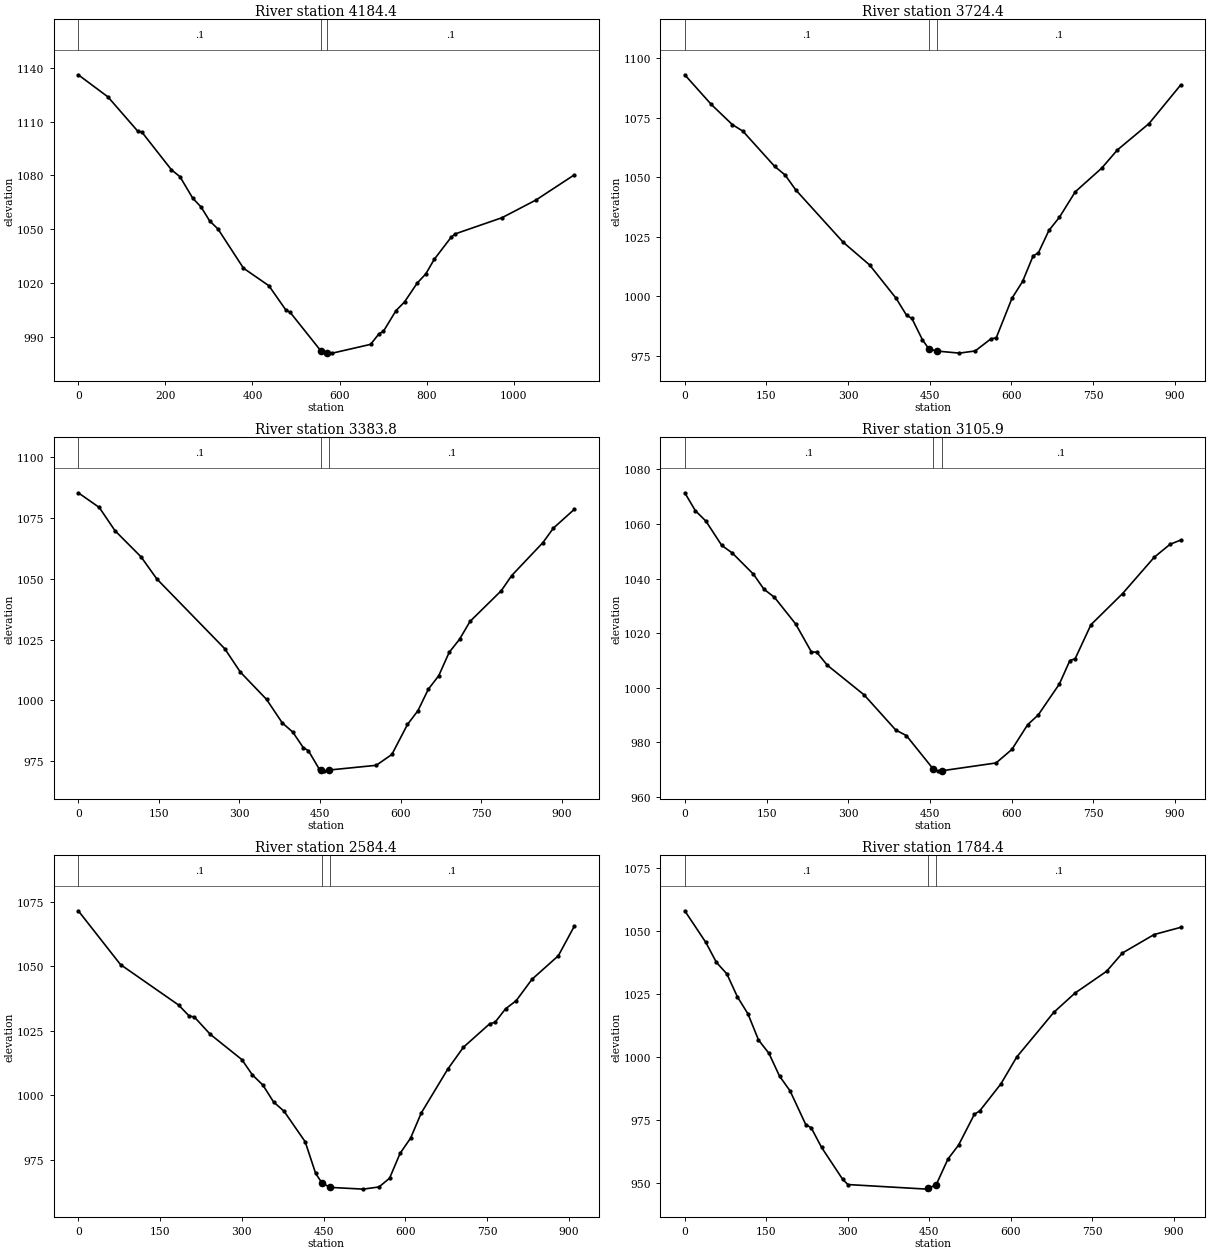
Type RM Length L Ch R = 1 ,4184.4,453.331,460,468.327
XS GIS Cut Line= 3
     1772591.708      334009.503     1772799.201      334534.252
     1773062.223      335045.395
#Sta/Elev= 30
       0 1136.04    68.1 1123.72   136.2 1104.70   145.9 1104.12   214.0 1083.04
   233.5 1079.22   262.7 1067.28   282.1 1062.27   301.6 1054.60   321.1 1049.96
   379.4 1028.19   437.8 1018.39   476.7 1004.89   486.5 1003.60   556.8  982.19
   571.8  981.04   583.8  980.81   671.5  985.70   690.9  991.67   700.7  992.90
   729.9 1004.55   749.4 1009.35   778.6 1019.91   798.1 1024.95   817.6 1033.10
   856.6 1045.48   866.3 1047.36   973.5 1056.36  1051.4 1066.22  1139.1 1080.18
#Mann= 3 , 0 , 0
       0     0.1       0   556.8   0.045       0   571.8     0.1       0
Bank Sta=   556.8,   571.8
Exp/Cntr=0.3,0.1

Type RM Length L Ch R = 1 ,3724.4,340.517,340.582,342.071
XS GIS Cut Line= 3
     1772416.292      334282.211     1772415.304      334738.093
     1772417.831      335192.930
#Sta/Elev= 30
       0 1093.09    48.5 1080.67    87.3 1072.17   106.7 1069.41   164.9 1054.64
   184.3 1050.97   203.7 1044.74   291.0 1022.70   339.5 1013.16   388.0  999.19
   407.4  991.99   417.1  990.69   436.5  981.71   448.2  977.92   463.2  976.98
   504.3  976.11   533.3  977.02   562.3  982.12   572.0  982.53   601.0  999.20
   620.4 1006.22   639.8 1016.99   649.4 1018.24   668.8 1027.69   688.1 1033.23
   717.2 1043.93   765.6 1053.84   794.6 1061.53   852.7 1072.61   910.7 1088.80
#Mann= 3 , 0 , 0
       0     0.1       0   448.2   0.045       0   463.2     0.1       0
Bank Sta=   448.2,   463.2
Exp/Cntr=0.3,0.1

Type RM Length L Ch R = 1 ,3383.8,283.19,277.939,271.146
XS GIS Cut Line= 3
     1772101.343      334269.584     1772094.465      334727.167
     1772063.513      335191.651
#Sta/Elev= 30
       0 1085.34    38.9 1079.34    68.2 1069.78   116.8 1059.01   146.1 1049.94
   272.6 1021.24   301.8 1011.59   350.5 1000.38   379.7  990.74   399.2  986.97
   418.7  980.61   428.4  979.29   447.9  971.98   452.4  971.48   457.6  970.91
   467.4  971.37   554.6  973.30   583.7  977.76   612.8  990.10   632.2  995.73
   651.6 1004.59   671.0 1010.15   690.4 1019.74   709.8 1025.15   729.2 1032.46
   787.4 1045.09   806.8 1051.32   865.0 1064.89   884.4 1070.82   923.1 1078.50
#Mann= 3 , 0 , 0
       0     0.1       0   452.4   0.045       0   467.4     0.1       0
Bank Sta=   452.4,   467.4
Exp/Cntr=0.3,0.1

Type RM Length L Ch R = 1 ,3105.9,515.578,521.484,527.677
XS GIS Cut Line= 3
     1771723.695      334273.534     1771819.559      334718.451
     1771924.922      335161.061
#Sta/Elev= 30
       0 1071.41    19.4 1064.86    38.7 1061.06    67.8 1052.16    87.2 1049.36
   125.9 1041.63   145.3 1036.10   164.6 1033.14   203.4 1023.40   232.4 1013.14
   242.1 1013.04   261.5 1008.28   329.2  997.40   387.3  984.52   406.7  982.50
   456.4  970.16   464.8  969.48   471.4  969.60   571.3  972.47   600.3  977.41
   629.4  986.51   648.7  990.04   687.5 1001.38   706.8 1009.97   716.5 1010.65
   745.5 1023.10   803.6 1034.53   861.7 1047.82   890.7 1052.56   910.1 1054.10
#Mann= 3 , 0 , 0
       0     0.1       0   456.4   0.045       0   471.4     0.1       0
Bank Sta=   456.4,   471.4
Exp/Cntr=0.3,0.1

Type RM Length L Ch R = 1 ,2584.4,801.406,799.995,798.519
XS GIS Cut Line= 3
     1771322.149      334336.010     1771305.552      334790.707
     1771289.317      335245.417
#Sta/Elev= 30
       0 1071.43    77.4 1050.60   183.9 1034.95   203.3 1030.70   213.0 1030.28
   242.0 1023.60   300.1 1013.79   319.5 1007.84   338.8 1003.90   358.2  997.40
   377.6  993.76   416.3  981.96   435.6  969.65   447.5  965.87   462.5  964.26
   522.8  963.59   551.8  964.43   571.2  967.81   590.5  977.43   609.9  983.40
   629.3  993.06   677.7 1009.99   706.7 1018.56   755.1 1027.68   764.8 1028.24
   784.1 1033.47   803.5 1036.58   832.6 1044.90   881.0 1054.03   910.0 1065.37
#Mann= 3 , 0 , 0
       0     0.1       0   447.5   0.045       0   462.5     0.1       0
Bank Sta=   447.5,   462.5
Exp/Cntr=0.3,0.1

Type RM Length L Ch R = 1 ,1784.4,395.72,400,403.702
XS GIS Cut Line= 3
     1770504.781      334289.242     1770515.228      334744.543
     1770527.410      335201.986
#Sta/Elev= 30
       0 1058.09    38.8 1045.51    58.1 1037.63    77.5 1033.00    96.9 1023.88
   116.3 1017.13   135.7 1006.75   155.0 1001.41   174.4  992.38   193.8  986.52
   222.9  973.02   232.6  971.88   251.9  964.02   290.7  951.33   300.4  949.26
   445.7  947.44   447.9  947.71   462.9  949.18   484.6  959.42   504.1  964.94
   533.3  977.22   543.0  978.52   582.0  989.26   611.2  999.97   679.4 1017.71
   718.3 1025.35   776.7 1034.05   805.9 1041.33   864.3 1048.67   913.0 1051.51
#Mann= 3 , 0 , 0
       0     0.1       0   447.9   0.045       0   462.9     0.1       0
Bank Sta=   447.9,   462.9
Exp/Cntr=0.3,0.1

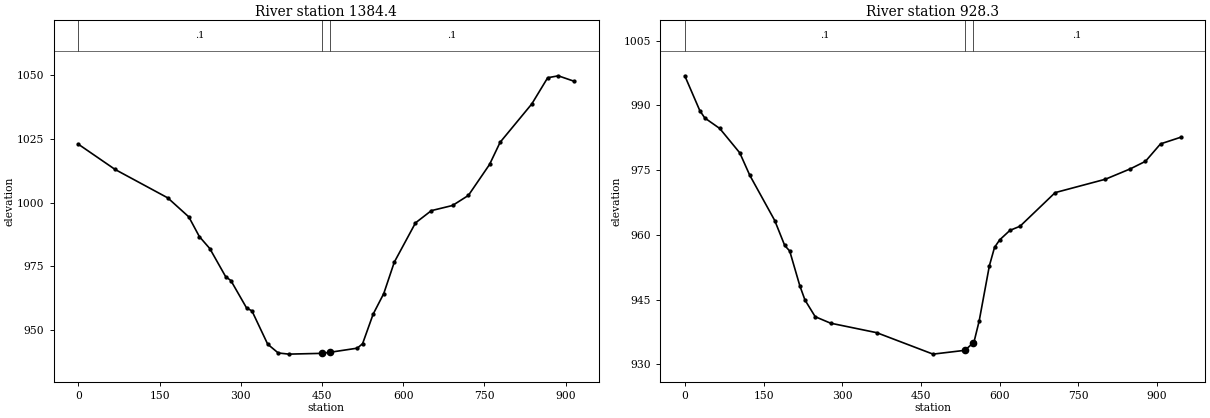
Type RM Length L Ch R = 1 ,1384.4,457.498,456.106,461.728
XS GIS Cut Line= 3
     1770199.951      334243.101     1770126.206      334693.803
     1770065.260      335148.922
#Sta/Elev= 30
       0 1022.95    68.0 1013.02   165.2 1001.87   204.1  994.40   223.5  986.69
   242.9  981.95   272.1  970.95   281.8  969.39   310.9  958.60   320.7  957.49
   349.8  944.41   369.2  940.97   388.7  940.51   449.2  940.81   464.2  941.21
   515.3  942.85   525.1  944.62   544.6  956.22   564.2  964.30   583.7  976.65
   622.8  992.05   652.1  996.86   691.2  998.88   720.5 1002.83   759.6 1014.99
   779.1 1023.69   837.7 1038.78   867.0 1049.05   886.6 1049.80   915.9 1047.66
#Mann= 3 , 0 , 0
       0     0.1       0   449.2   0.045       0   464.2     0.1       0
Bank Sta=   449.2,   464.2
Exp/Cntr=0.3,0.1

Type RM Length L Ch R = 1 ,928.3,918.546,928.294,931.69
XS GIS Cut Line= 4
     1770095.008      334205.470     1769893.836      334263.733
     1769685.140      334628.002     1769666.168      334942.944
#Sta/Elev= 30
       0  996.85    28.6  988.79    38.1  987.08    66.6  984.65   104.7  979.01
   123.8  973.81   171.4  963.32   190.4  957.54   199.9  956.26   219.2  948.20
   229.0  944.90   248.5  941.04   277.8  939.54   365.7  937.34   473.0  932.37
   533.7  933.25   548.7  934.88   551.2  935.25   560.9  940.04   580.4  952.86
   590.2  957.10   600.0  958.84   619.5  961.04   638.8  962.00   705.7  969.79
   801.4  972.89   849.2  975.31   877.8  977.04   906.5  981.08   944.8  982.61
#Mann= 3 , 0 , 0
       0     0.1       0   533.7   0.045       0   548.7     0.1       0
Bank Sta=   533.7,   548.7
Exp/Cntr=0.3,0.1